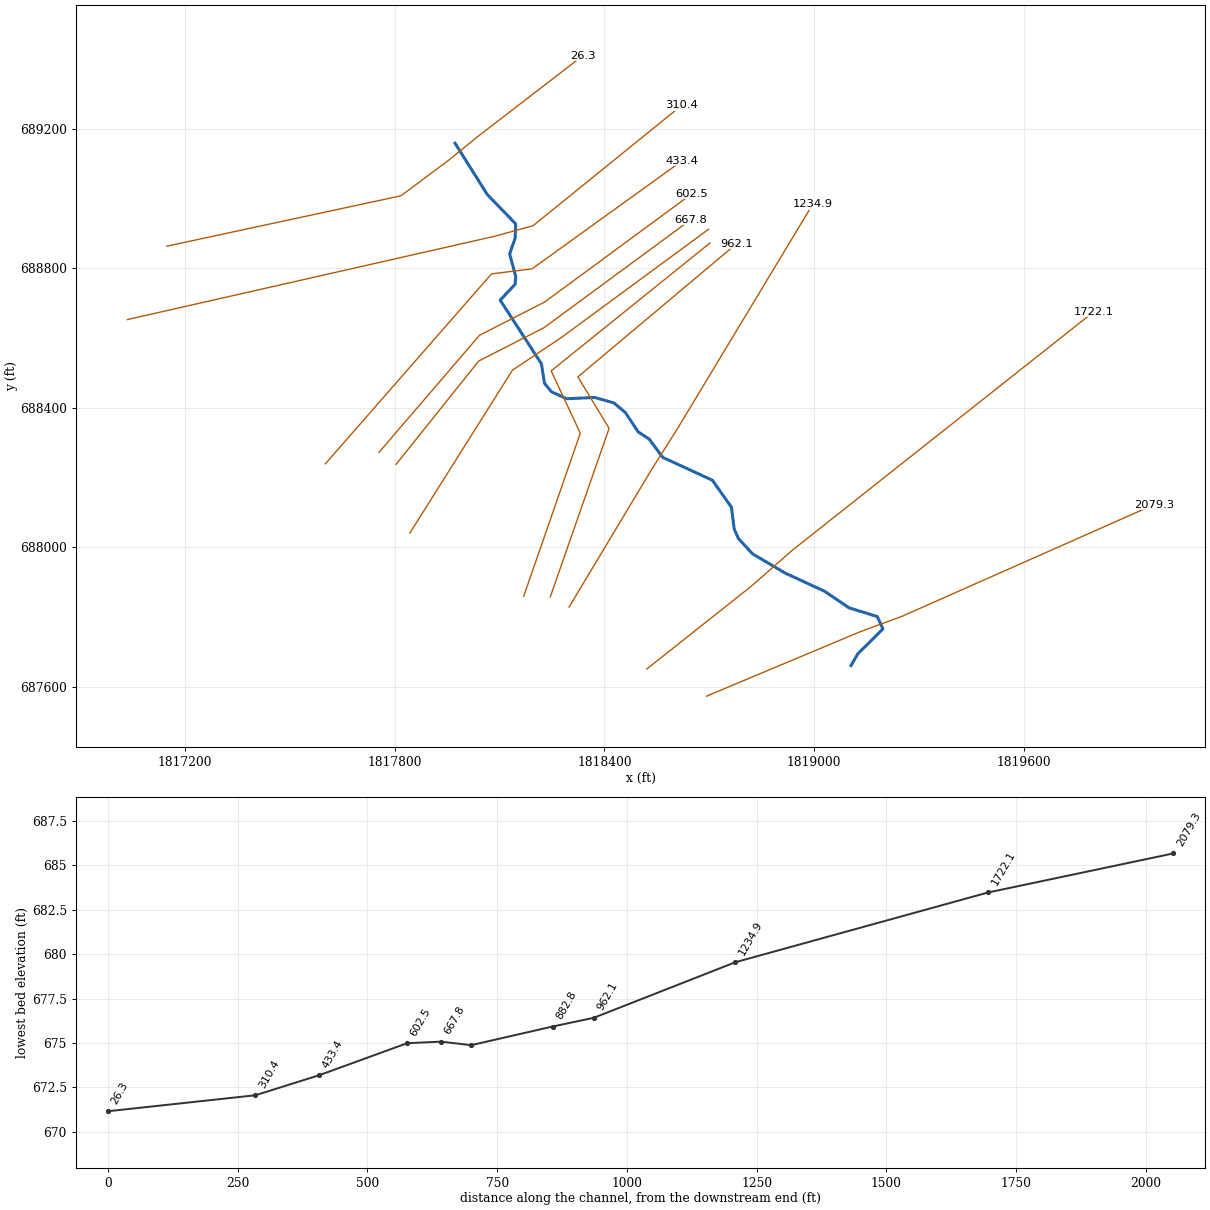
--- PattrsnRun.prj (project) ---

Proj Title=PattrsnRun
Current Plan=p01
Default Exp/Contr=0,0
English Units
Geom File=g01
Flow File=f01
Plan File=p01
BEGIN DESCRIPTION:
AMEC Environment & Infrastructure, 2013
Projection: NAD 1983 State Plane West Virginia South FIPS 4702 (US Feet)
Vertical Datum: NAVD 1988
END DESCRIPTION:
DSS Export Rating Curves= 0
DSS Export Rating Curve Sorted= 0
DSS Export Volume Flow Curves= 0
DXF OffsetX= 0
DXF OffsetY= 0
DXF ScaleX= 0
DXF ScaleY= 0

--- PattrsnRun.p01 (plan) ---

Plan Title=Floodplain
Program Version=4.00
Geom File=g01
Flow File=f01
K Sum by GR=0
Std Step Tol=0.01
Critical Tol=0.01
Num of Std Step Trials=20
Max Error Tol=0.3
Flow Tol Ratio=0.001
Split Flow NTrial=30
Split Flow Tol=0.02
Split Flow Ratio=0.02
Log Output Level=0
Friction Slope Method=1
Unsteady Friction Slope Method=2
Unsteady Bridges Friction Slope Method=1
Global Log Level=0
CheckData=False
Run HTab=0
Run UNet=0
Run PostProcess=0
UNET Theta=0
UNET Theta Warmup=0
UNET ZTol=0
UNET ZSATol=0
UNET MxIter=0
UNET MaxInSteps=0
UNET DtIC=0
UNET DtMin=0
UNET MaxCRTS=0
UNET WFStab=0
UNET SFStab=0
UNET WFX=0
UNET SFX=0
UNET DSS MLevel=0
UNET DZMax Abort=0
UNET Convert EG Bridges=0
UNET Use Existing IB Tables=0
UNET Froude Limit=0
UNET Froude Power=0
Write IC File=0
Echo Input=False
Echo Output=False
Write Detailed=0

--- PattrsnRun.f01 (steady flow) ---

Flow Title=NFF Regression Equation
Program Version=4.10
Number of Profiles= 1
Profile Names=P100yr
River Rch & RM=PattrsnRun,Main            ,2079.3
985.0382
River Rch & RM=PattrsnRun,Main            ,433.4
1030.134
River Rch & RM=PattrsnRun,Main            ,310.4
1313.269
Boundary for River Rch & Prof#=PattrsnRun,Main            , 1
Up Type= 0
Dn Type= 3
Dn Slope=0.00307
DSS Import GetInterval= 0
DSS Import GetPeak= 0
DSS Import FillOption= 0

--- PattrsnRun.g01 (geometry) ---

Geom Title=USGS 3m DEM
Program Version=4.10

River Reach=PattrsnRun      ,Main
Reach XY= 30
     1819105.695      687660.776     1819125.559      687695.065
     1819196.998      687765.666     1819180.908      687801.229
     1819099.772      687826.402     1819030.021      687873.943
     1818917.127      687926.036     1818823.337      687981.604
     1818783.387       688025.02     1818771.228      688052.807
     1818763.298      688115.004     1818708.629      688192.496
     1818567.023      688257.747     1818527.723      688310.777
     1818496.473      688330.742     1818460.015      688386.298
     1818427.029      688414.076     1818372.341      688429.701
     1818291.612      688426.229      1818248.21      688446.194
     1818228.244      688470.499     1818219.491      688526.384
     1818101.421      688708.954     1818144.194      688754.404
     1818145.929      688776.982     1818128.555       688841.24
     1818144.182      688886.398     1818145.829      688927.765
     1818064.701      689011.655     1817972.218      689159.054

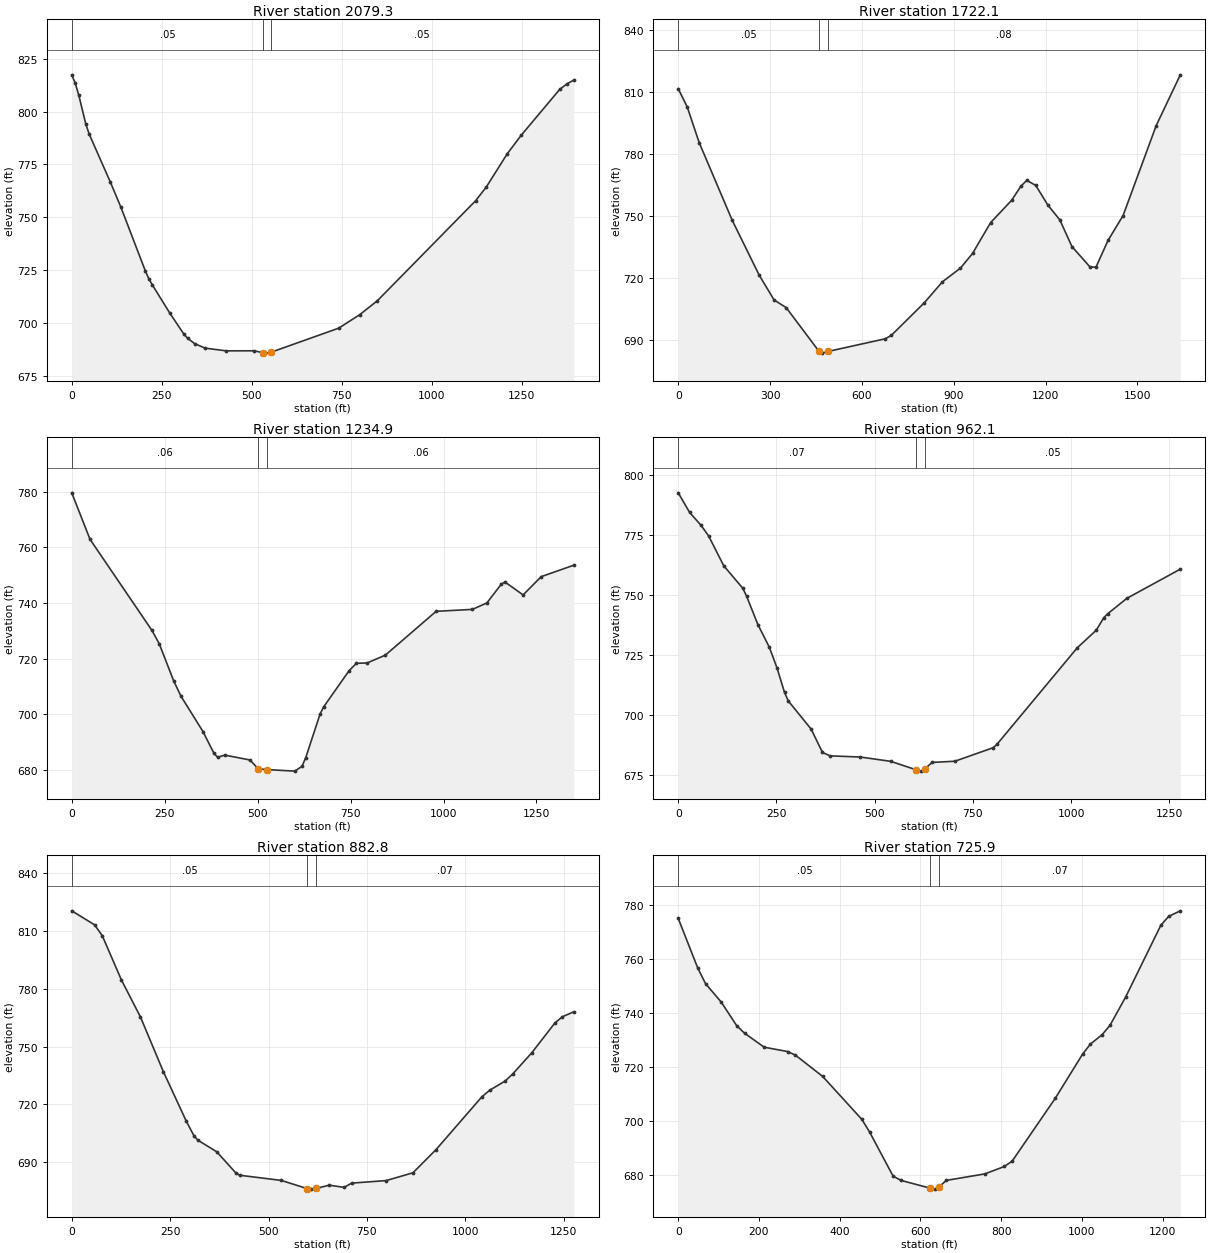
Type RM Length L Ch R = 1 ,2079.3  ,348.4,357.1,365.3
XS GIS Cut Line= 4
     1818691.873       687572.93     1819131.977      687757.826
     1819251.769      687802.097     1819973.123      688122.409
#Sta/Elev= 30
       0  817.46     9.7  813.46    19.5   807.8      39  794.14    48.7  789.26
   107.2  766.65   136.4   754.8   204.6  724.48   214.3   720.8   224.1  717.89
   272.8  704.48   311.8  694.57   321.5  692.77     341   690.2   370.2  688.05
   428.7  686.76   506.8  686.78  532.03  685.83   536.3  685.68   552.4  686.04
   741.5  697.51     800  703.92   848.7  710.48  1121.5  757.82  1150.8  764.22
  1209.2  780.01  1248.2  788.85  1355.4  810.62  1374.9  813.14  1394.4  814.99
#Mann= 3 , 0 , 0
       0     .05       0  532.03    .045       0   552.4     .05       0
Bank Sta=532.03,552.4
XS Rating Curve= 0 ,0
Exp/Cntr=0.3,0.1

Type RM Length L Ch R = 1 ,1722.1  ,479.9,487.2,493.3
XS GIS Cut Line= 4
       1818521.3      687651.055     1818820.345      687888.468
     1818937.966      687991.767     1819801.248      688676.229
#Sta/Elev= 30
       0  811.63    29.4   802.8    68.5  785.49   176.2  747.91   264.3  721.33
   313.3  709.21   352.5  705.58   460.1   684.3   469.9  683.48   489.4   684.3
   676.1  690.43   695.8  692.04     804  707.92     863  718.05     922  724.71
   961.3  731.78  1020.4  746.73  1089.2  757.58  1118.7  764.26  1138.4  767.23
  1167.9  764.78  1207.3  755.26  1246.6  748.06    1286  735.16    1345  725.26
  1364.6  725.14    1404  738.11  1453.2  750.18  1561.4  793.79  1640.1  818.38
#Mann= 3 , 0 , 0
       0     .05       0   460.1    .045       0   489.4     .08       0
Bank Sta=460.1,489.4
XS Rating Curve= 0 ,0
Exp/Cntr=0.3,0.1

Type RM Length L Ch R = 1 ,1234.9  ,247.5,272.9,297.8
XS GIS Cut Line= 4
     1818298.644      687828.572     1818535.382      688223.875
     1818609.643      688341.561      1818996.56      688984.822
#Sta/Elev= 30
       0  779.64      49  762.94   215.7  730.15   235.3  725.36   274.5  711.89
   294.1  706.42   352.9  693.79   382.3     686   392.2  684.54   411.8  685.31
   479.3  683.56   501.8  680.37   525.7   680.1   599.9  679.55   619.4  681.29
   629.2  684.31   668.2  700.19   677.9  702.72   746.2  715.71   765.7  718.33
   794.9  718.47   843.6  721.27   980.1  737.02  1077.6  737.72  1116.6  740.02
  1155.6  746.82  1165.4  747.56  1214.1  742.92  1262.8  749.49  1350.6  753.62
#Mann= 3 , 0 , 0
       0     .06       0   501.8    .045       0   525.7     .06       0
Bank Sta=501.8,525.7
XS Rating Curve= 0 ,0
Exp/Cntr=0.3,0.1

Type RM Length L Ch R = 1 ,962.1   ,78.6,79.2,83.1
XS GIS Cut Line= 4
     1818244.824      687857.652     1818413.227      688341.159
     1818323.817      688488.729      1818777.81      688870.673
#Sta/Elev= 30
       0  792.42      29  784.24      58  778.89    77.3  774.46   115.9     762
   164.2  752.66   173.9  749.36   202.9  737.45   231.8  728.08   251.2  719.53
   270.5  709.22   280.2  705.65   338.1  693.97   367.1  684.22   386.4  682.79
   463.7  682.29   540.8   680.5   605.7  676.96   617.4  676.42     627   677.3
   646.2  680.05     704  680.54   801.2  686.16     811  687.56  1015.2  727.77
  1063.8  735.14  1083.3  740.44    1093  742.01  1141.7  748.44  1277.8  760.61
#Mann= 3 , 0 , 0
       0     .07       0   605.7    .045       0     627     .05       0
Bank Sta=605.7,627
XS Rating Curve= 0 ,0
Exp/Cntr=0.3,0.1

Type RM Length L Ch R = 1 ,882.8   ,192.8,156.9,117.7
XS GIS Cut Line= 4
     1818168.869      687859.822     1818330.762       688327.27
     1818247.428       688506.09     1818701.855      688872.843
#Sta/Elev= 30
       0  820.46    58.2  813.16    77.6  807.49   126.1  784.59   174.6  765.32
   232.8  736.92     291  711.22   310.4   703.7   320.1   701.4   368.6   695.3
   417.1  684.29   426.8  683.14   532.3  680.46     598  676.22   607.4  675.93
  620.65  676.29   654.4  677.98     692  676.84   711.4  679.05     799  680.37
   867.2  684.43   925.6  696.44  1042.4  723.92  1061.8  727.25  1100.8     732
  1120.2  735.65  1168.9  746.72  1227.3  762.09  1246.7  765.45  1275.9  768.03
#Mann= 3 , 0 , 0
       0     .05       0     598    .045       0  620.65     .07       0
Bank Sta=598,620.65
XS Rating Curve= 0 ,0
Exp/Cntr=0.3,0.1

Type RM Length L Ch R = 1 ,725.9   ,60.8,58.2,55.6
XS GIS Cut Line= 4
     1817842.914      688040.812     1818136.317      688507.826
     1818276.942       688602.01     1818697.949       688912.34
#Sta/Elev= 30
       0  775.04    48.4  756.66    67.7  750.89   106.4   744.1   145.1  735.29
   164.5  732.55   212.9  727.39   270.9  725.78   290.3  724.46     358  716.55
   454.8   700.7   474.1  696.01   532.2  679.71   551.5  678.13   624.9   675.2
   636.2  674.88   645.6   675.7   664.4  678.12   759.5  680.51     808  683.26
   827.3  685.25   933.9  708.46  1001.7  724.81    1021  728.53  1050.1  732.02
  1069.5  735.46  1108.2   745.9  1195.4  772.45  1214.8  775.77  1243.8  777.84
#Mann= 3 , 0 , 0
       0     .05       0   624.9    .045       0   645.6     .07       0
Bank Sta=624.9,645.6
XS Rating Curve= 0 ,0
Exp/Cntr=0.3,0.1

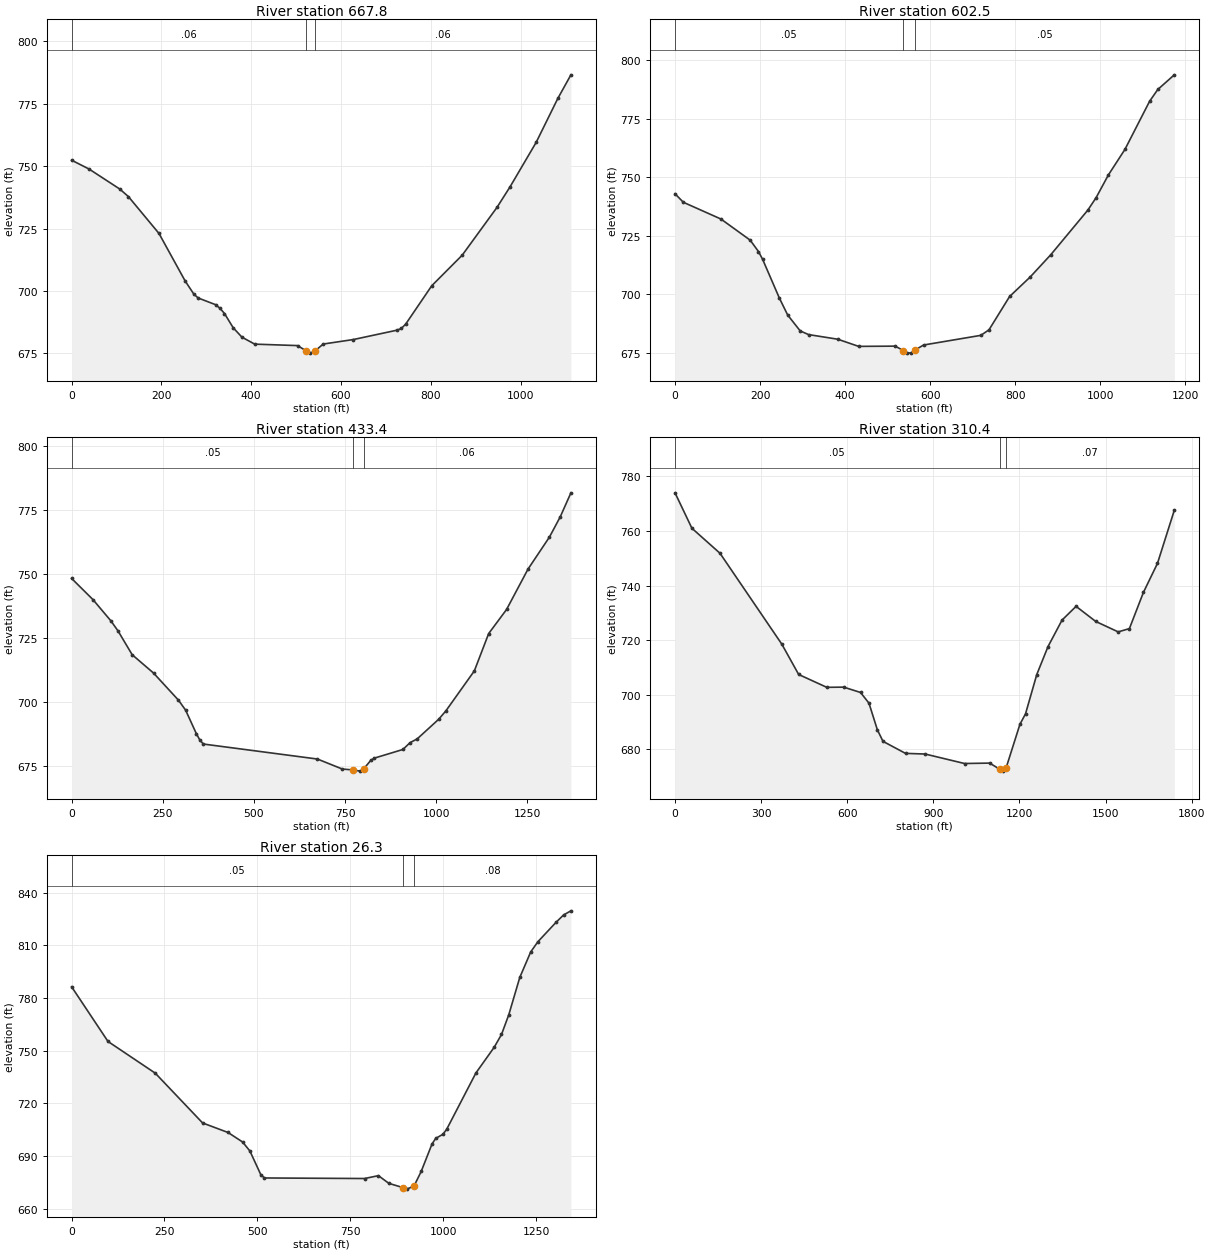
Type RM Length L Ch R = 1 ,667.8   ,65.2,65.2,65
XS GIS Cut Line= 4
     1817803.418       688237.86     1818039.963      688534.301
     1818226.595      688629.788     1818647.602      688940.117
#Sta/Elev= 30
       0  752.37    38.9  748.82     107  740.84   126.4   737.8   194.5  723.03
   252.8  703.99   272.3  698.68     282  697.15   320.9  694.47   330.6  692.99
   340.4  690.95   359.8  685.24   379.2  681.48   407.8  678.68   503.1   678.1
   521.6  676.07   531.7  675.08   541.2  675.84   560.3  678.72   627.6  680.53
   724.5  684.27   734.2  684.95   743.9   686.7     802  702.08   869.8  714.32
   947.3  733.47   976.3  741.69  1034.4  759.48  1082.9  777.17  1111.9  786.57
#Mann= 3 , 0 , 0
       0     .06       0   521.6    .045       0   541.2     .06       0
Bank Sta=521.6,541.2
XS Rating Curve= 0 ,0
Exp/Cntr=0.3,0.1

Type RM Length L Ch R = 1 ,602.5   ,178.4,169.2,157.1
XS GIS Cut Line= 4
     1817754.807      688272.583     1818042.133      688608.086
     1818228.765      688703.572     1818649.772      689013.902
#Sta/Elev= 30
       0  742.95    19.6  739.32     108  732.18   176.7  723.18   196.3  718.32
   206.1  714.96   245.4  698.48     265  691.23   294.5  684.45   314.1   682.9
   382.8  680.92   431.9  677.87     518  677.97     537   676.1   546.5  674.99
   556.1  675.13   565.6  676.44   584.7  678.45   719.2  682.57   738.5  684.93
     787  699.15   835.4  707.46   883.8  716.95     971  735.99   990.4  741.28
  1019.4  751.01  1058.2  761.86  1116.3  782.42  1135.6  787.44  1174.4  793.68
#Mann= 3 , 0 , 0
       0     .05       0     537    .045       0   565.6     .05       0
Bank Sta=537,565.6
XS Rating Curve= 0 ,0
Exp/Cntr=0.3,0.1

Type RM Length L Ch R = 1 ,433.4   ,119.1,123,126.9
XS GIS Cut Line= 4
     1817601.161      688239.597     1818076.638      688784.301
     1818192.524      688798.624     1818621.994       689108.52
#Sta/Elev= 30
       0  748.24    58.6  739.99   107.5  731.76     127  727.86   166.1  718.53
   224.7  711.39   293.1  700.82   312.7  696.93     342   687.8   351.8  685.26
   361.5  683.74   674.2   677.9   742.5     674   771.7  673.66   791.2  673.19
   800.9  674.03   820.3  677.36   830.1  678.25   908.5  681.62   928.1  684.27
   947.7  685.74  1006.5  693.36  1026.2  696.61  1104.6  712.26  1143.8  726.77
  1192.9  736.16  1251.7  751.88  1310.6  764.39    1340  772.22  1369.4   781.6
#Mann= 3 , 0 , 0
       0     .05       0   771.7    .045       0   800.9     .06       0
Bank Sta=771.7,800.9
XS Rating Curve= 0 ,0
Exp/Cntr=0.3,0.1

Type RM Length L Ch R = 1 ,310.4   ,274.7,284.1,292.9
XS GIS Cut Line= 4
     1817034.321      688653.225     1818084.668       688891.94
     1818195.345      688922.322     1818620.692      689267.374
#Sta/Elev= 30
       0  773.95    58.8  760.98   156.7  751.82   372.1  718.54   430.8  707.44
   528.8  702.74   587.5  702.81   646.3  700.86   675.7  696.95     705  687.18
   724.6  682.96     803  678.56   871.5  678.32  1008.6  674.85  1096.3     675
 1130.71  672.79  1144.1  672.06  1153.6  673.27  1201.7  689.21  1221.2  693.05
  1260.4  707.43  1299.5  717.65  1348.4  727.36  1397.3  732.39  1465.8  726.86
    1544  723.04  1583.1  724.24    1632  737.51  1680.9  748.12  1739.6  767.58
#Mann= 3 , 0 , 0
       0     .05       0 1130.71    .045       0  1153.6     .07       0
Bank Sta=1130.71,1153.6
XS Rating Curve= 0 ,0
Exp/Cntr=0.3,0.1

Type RM Length L Ch R = 1 ,26.3    ,28,26.3,24.6
XS GIS Cut Line= 5
     1817147.168      688863.729     1817817.293      689008.251
     1817952.289      689108.954     1818034.755      689176.229
     1818338.574      689410.604
#Sta/Elev= 30
       0  786.42    97.9  755.28   225.2  737.21   352.6  708.85   421.1  703.42
   460.3     698   479.9  692.88   509.2  679.43     519  677.52   788.5   677.2
   825.9  678.83     854  674.45   891.6  672.05   902.3  671.16   921.7  672.91
     941  681.21   970.2   696.9   980.1  700.04   999.7  702.43  1009.6  705.22
  1088.3  737.32  1137.5  751.96  1157.2  759.25  1176.8  770.47  1206.4  791.73
  1235.9   806.3  1255.5  812.17  1304.7   823.3  1324.4  827.35  1344.1   829.7
#Mann= 3 , 0 , 0
       0     .05       0   891.6    .045       0   921.7     .08       0
Bank Sta=891.6,921.7
XS Rating Curve= 0 ,0
Exp/Cntr=0.3,0.1

Chan Stop Cuts=-1
Use User Specified Reach Order=0
Composite Channel Slope=5